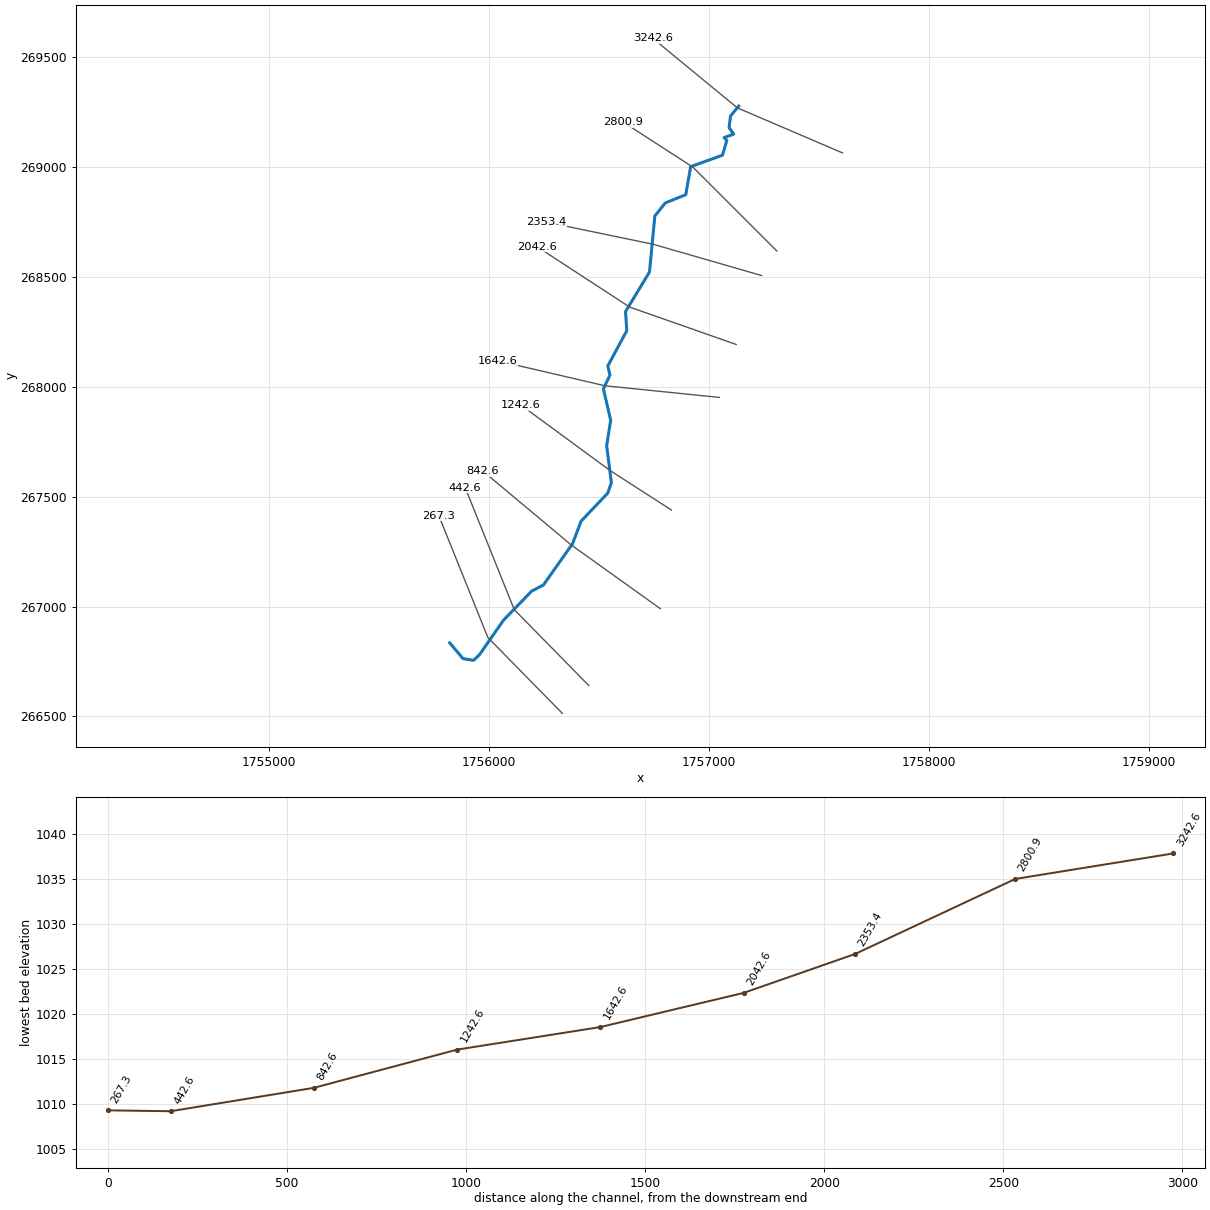
--- BrshyFTr2.prj (project) ---

Proj Title=BrshyFTr2
Current Plan=p01
Geom File=g01
Flow File=f01
Plan File=p01
DSS Export Rating Curves=0
DSS Export Rating Curve Sorted=0
DSS Export Volume Flow Curves=0
DXF OffsetX=0
DXF OffsetY=0
DXF ScaleX=0
DXF ScaleY=0

--- BrshyFTr2.p01 (plan) ---

Plan Title=Floodplain
Program Version=4.00
Geom File=g01
Flow File=f01
K Sum by GR=0
Std Step Tol=0.01
Critical Tol=0.01
Num of Std Step Trials=20
Max Error Tol=0.3
Flow Tol Ratio=0.001
Split Flow NTrial=30
Split Flow Tol=0.02
Split Flow Ratio=0.02
Log Output Level=0
Friction Slope Method=1
Unsteady Friction Slope Method=2
Unsteady Bridges Friction Slope Method=1
Global Log Level=0
CheckData=False
Run HTab=0
Run UNet=0
Run PostProcess=0
UNET Theta=0
UNET Theta Warmup=0
UNET ZTol=0
UNET ZSATol=0
UNET MxIter=0
UNET MaxInSteps=0
UNET DtIC=0
UNET DtMin=0
UNET MaxCRTS=0
UNET WFStab=0
UNET SFStab=0
UNET WFX=0
UNET SFX=0
UNET DSS MLevel=0
UNET DZMax Abort=0
UNET Convert EG Bridges=0
UNET Use Existing IB Tables=0
UNET Froude Limit=0
UNET Froude Power=0
Write IC File=0
Echo Input=False
Echo Output=False
Write Detailed=0

--- BrshyFTr2.f01 (steady flow) ---

Flow Title=NFF Regression Equation
Program Version=4.00
Number of Profiles=1
Profile Names=P100yr
River Rch & RM=BrshyFTr2,Main      ,3242.6
726.2800
River Rch & RM=BrshyFTr2,Main      ,2353.4
800.5936
River Rch & RM=BrshyFTr2,Main      ,267.3
862.8900
Boundary for River Rch & Prof#=BrshyFTr2,Main      ,1
Up Type=0
Dn Type=3
Dn Slope=0.00624

--- BrshyFTr2.g01 (geometry) ---

Geom Title=USGS 3m DEM
Program Version=4.00

River Reach=BrshyFTr2     ,Main
Reach XY= 30
     1757135.742      269278.594     1757098.522      269232.915
     1757092.319      269180.469     1757113.185      269151.144
     1757069.598      269135.261     1757081.927      269122.213
     1757062.284      269055.258     1756917.758      269002.916
     1756895.381      268875.271     1756802.680      268837.935
     1756754.953      268778.336     1756730.620      268523.349
     1756621.765      268342.887     1756627.572      268256.290
     1756541.439      268096.118     1756551.050      268054.391
     1756521.336      267991.388     1756554.513      267847.916
     1756535.940      267733.531     1756557.492      267564.812
     1756541.423      267517.140     1756419.873      267389.185
     1756381.089      267286.480     1756248.523      267098.252
     1756195.693      267070.941     1756067.191      266938.036
     1755957.787      266780.587     1755931.249      266755.833
     1755883.414      266763.297     1755823.354      266835.178

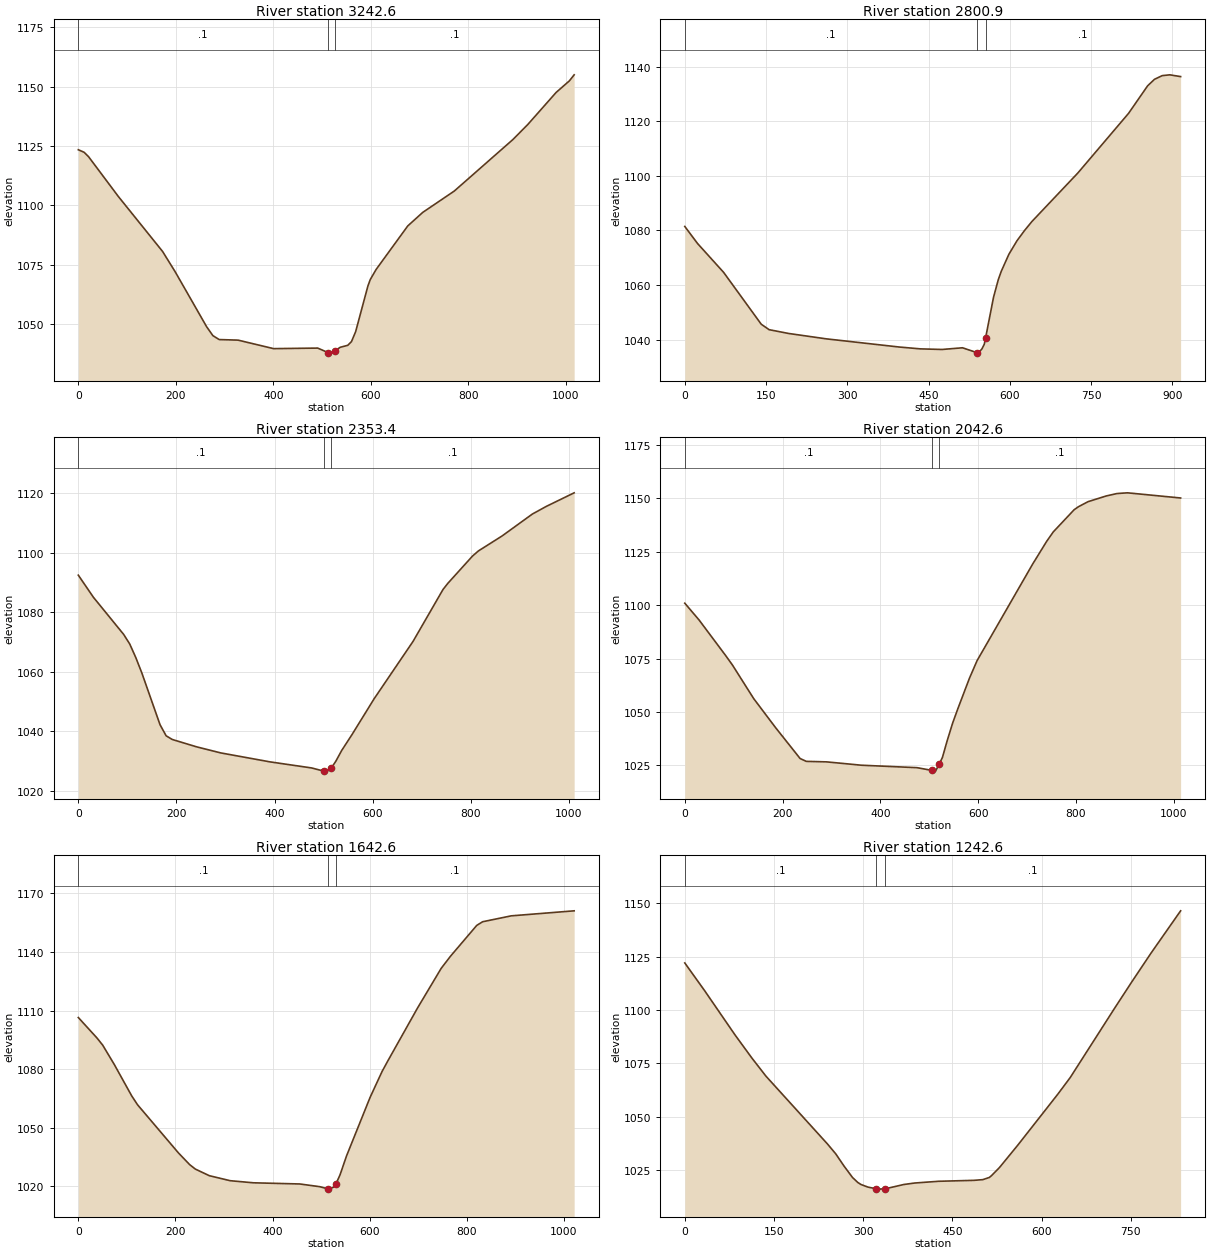
Type RM Length L Ch R = 1 ,3242.6,420.322,441.678,410.465
XS GIS Cut Line= 3
     1757607.072      269065.752     1757129.667      269270.650
     1756745.742      269587.131
#Sta/Elev= 30
       0 1123.47    11.8 1122.41    20.9 1120.57    82.3 1103.74   172.7 1080.69
   198.5 1072.16   263.1 1048.99   276.1 1045.20   289.0 1043.56   327.7 1043.32
   400.6 1039.74   491.0 1039.97     512 1038.10   518.1 1037.85     527 1038.95
   537.3 1040.31   552.7 1041.14   560.3 1042.70   568.8 1046.84   594.1 1066.18
   598.9 1068.84   610.9 1073.09   675.8 1091.40   706.6 1097.11   771.2 1106.08
   891.2 1127.72   922.0 1134.10   980.2 1147.61  1007.3 1152.47  1017.1 1155.01
#Mann= 3 , 0 , 0
       0     0.1       0     512   0.045       0     527     0.1       0
Bank Sta=     512,     527
Exp/Cntr=0.3,0.1

Type RM Length L Ch R = 1 ,2800.9,437.826,447.516,455.339
XS GIS Cut Line= 3
     1757309.004      268619.323     1756928.037      269000.727
     1756612.453      269204.998
#Sta/Elev= 30
       0 1081.45    23.5 1075.21    71.6 1064.63   141.1 1045.60   155.6 1043.61
   191.5 1042.22   260.8 1040.25   395.1 1037.26   434.9 1036.57   474.8 1036.35
   512.5 1036.97     540 1035.13   541.5 1035.01   548.2 1036.52   552.7 1038.28
     555 1040.50   569.8 1055.55   578.5 1061.92   584.0 1065.00   598.1 1071.26
   612.8 1076.14   626.4 1079.82   640.5 1083.25   725.4 1101.06   818.9 1122.91
   854.1 1133.01   866.8 1135.40   881.0 1136.74   895.1 1137.04   915.0 1136.39
#Mann= 3 , 0 , 0
       0     0.1       0     540   0.045       0     555     0.1       0
Bank Sta=     540,     555
Exp/Cntr=0.3,0.1

Type RM Length L Ch R = 1 ,2353.4,311.79,310.806,302.733
XS GIS Cut Line= 3
     1757240.402      268507.112     1756748.247      268649.473
     1756259.973      268750.836
#Sta/Elev= 30
       0 1092.42    30.7 1085.02    92.5 1072.53   104.9 1069.30   117.2 1064.77
   129.6 1059.56   166.6 1042.24   179.0 1038.52   191.4 1037.29   240.8 1034.83
   290.2 1032.78   391.1 1029.76   475.6 1027.73   500.3 1026.67   500.4 1026.66
   512.7 1026.97   515.3 1027.60   524.8 1029.91   537.0 1033.59   558.7 1039.10
   603.0 1050.91   682.5 1070.20   743.6 1087.62   753.7 1089.73   803.7 1098.83
   815.8 1100.56   864.1 1105.59   925.9 1112.95   954.5 1115.53  1011.0 1120.06
#Mann= 3 , 0 , 0
       0     0.1       0   500.3   0.045       0   515.3     0.1       0
Bank Sta=   500.3,   515.3
Exp/Cntr=0.3,0.1

Type RM Length L Ch R = 1 ,2042.6,393.946,400,408.653
XS GIS Cut Line= 3
     1757124.639      268193.486     1756640.613      268363.723
     1756220.828      268637.997
#Sta/Elev= 30
       0 1100.94    29.3 1093.05    83.9 1076.33    97.3 1072.05   141.0 1056.25
   185.4 1042.77   235.8 1028.24   248.4 1026.91   290.0 1026.67   361.6 1025.10
   474.9 1023.96   505.6 1022.67   512.7 1022.34   520.6 1025.74   526.8 1028.73
   536.3 1036.38   547.7 1044.83   558.0 1051.33   582.0 1065.78   597.7 1074.07
   711.1 1119.16   739.5 1129.72   753.4 1134.28   796.2 1144.70   805.0 1146.10
   824.6 1148.46   861.9 1151.14   883.6 1152.26   905.3 1152.60  1013.9 1150.18
#Mann= 3 , 0 , 0
       0     0.1       0   505.6   0.045       0   520.6     0.1       0
Bank Sta=   505.6,   520.6
Exp/Cntr=0.3,0.1

Type RM Length L Ch R = 1 ,1642.6,413.543,400,386.723
XS GIS Cut Line= 3
     1757047.130      267952.479     1756527.465      268005.721
     1756041.931      268118.931
#Sta/Elev= 30
       0 1106.41    38.3 1095.97    50.2 1092.27    74.1 1082.34   109.9 1066.29
   121.8 1061.78   206.0 1037.12   229.2 1031.09   241.1 1028.78   269.7 1025.42
   312.8 1022.85   360.5 1021.78   456.0 1021.18   497.1 1019.79   514.9 1018.59
   515.6 1018.54   527.7 1019.77   529.9 1020.95   538.8 1025.81   552.1 1035.46
   600.8 1065.56   625.2 1078.68   637.4 1084.26   698.4 1111.28   747.1 1131.59
   766.2 1137.78   820.3 1153.58   832.5 1155.46   891.4 1158.48  1020.9 1161.05
#Mann= 3 , 0 , 0
       0     0.1       0   514.9   0.045       0   529.9     0.1       0
Bank Sta=   514.9,   529.9
Exp/Cntr=0.3,0.1

Type RM Length L Ch R = 1 ,1242.6,397.331,400,403.736
XS GIS Cut Line= 3
     1756830.547      267439.665     1756553.473      267618.384
     1756147.458      267917.004
#Sta/Elev= 30
       0 1122.11    33.2 1109.17    84.2 1088.46   112.5 1077.63   136.3 1069.07
   239.7 1037.27   253.8 1032.58   267.9 1026.79   282.0 1021.49   290.8 1019.17
   296.2 1018.21   308.0 1016.98   322.2 1016.18   324.4 1016.03   337.2 1016.19
   368.4 1018.21   386.8 1018.90   426.9 1019.71   486.3 1020.15   501.1 1020.48
   512.1 1021.51   515.8 1022.38   529.1 1026.15   560.0 1036.69   627.3 1060.60
   648.0 1068.33   722.1 1100.62   751.6 1113.24   783.8 1126.67   833.7 1146.56
#Mann= 3 , 0 , 0
       0     0.1       0   322.2   0.045       0   337.2     0.1       0
Bank Sta=   322.2,   337.2
Exp/Cntr=0.3,0.1

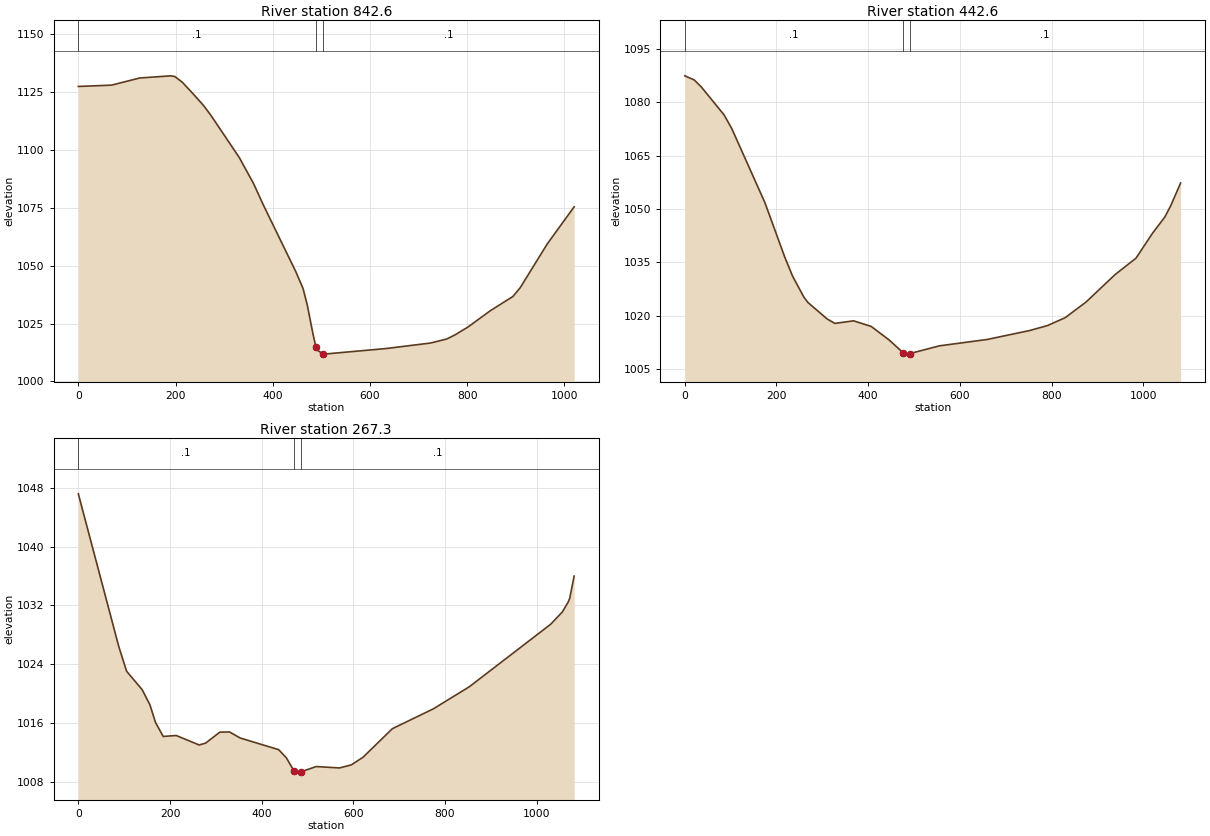
Type RM Length L Ch R = 1 ,842.6,404.011,400,388.351
XS GIS Cut Line= 3
     1756779.586      266991.036     1756376.163      267280.124
     1755974.539      267616.495
#Sta/Elev= 30
       0 1127.52    68.2 1128.08   126.6 1131.18   190.3 1132.11   198.8 1131.78
   214.3 1129.28   238.3 1123.84   258.1 1119.16   272.7 1115.06   331.1 1096.80
   360.3 1085.62   380.9 1076.18   448.0 1047.22   462.5 1040.06   471.0 1033.10
   482.9 1020.43   488.8 1014.90   491.8 1013.48   503.8 1011.83   505.0 1011.78
   632.0 1014.17   724.5 1016.57   757.8 1018.30   774.7 1020.06   801.3 1023.44
   847.7 1030.55   894.2 1036.71   909.4 1040.56   964.9 1059.44  1020.2 1075.48
#Mann= 3 , 0 , 0
       0     0.1       0   488.8   0.045       0   503.8     0.1       0
Bank Sta=   488.8,   503.8
Exp/Cntr=0.3,0.1

Type RM Length L Ch R = 1 ,442.6,175.255,175.256,177.169
XS GIS Cut Line= 3
     1756454.612      266641.168     1756116.433      266986.288
     1755893.338      267541.752
#Sta/Elev= 30
       0 1087.46    20.6 1086.30    35.9 1084.35    85.7 1076.47   102.4 1072.65
   174.7 1051.81   218.7 1036.27   235.3 1031.08   259.5 1025.28   268.6 1023.71
   310.4 1019.09   327.4 1017.82   368.3 1018.55   406.8 1016.96   446.1 1013.13
   475.7 1009.62   482.4 1009.18   490.7 1009.32   555.3 1011.51   660.1 1013.31
   753.0 1015.84   791.4 1017.22   829.7 1019.42   874.8 1023.77   938.7 1031.55
   984.3 1036.17  1020.8 1043.26  1047.2 1047.74  1060.0 1050.88  1081.7 1057.32
#Mann= 3 , 0 , 0
       0     0.1       0   475.7   0.045       0   490.7     0.1       0
Bank Sta=   475.7,   490.7
Exp/Cntr=0.3,0.1

Type RM Length L Ch R = 1 ,267.3,304.352,267.334,237.741
XS GIS Cut Line= 3
     1756334.770      266514.136     1755996.591      266859.256
     1755773.497      267414.720
#Sta/Elev= 30
       0 1047.20    88.3 1026.38   105.3 1023.03   139.2 1020.52   156.1 1018.47
   168.4 1016.05   185.2 1014.14   213.7 1014.27   263.6 1012.98   277.6 1013.23
   308.8 1014.73   330.1 1014.75   353.1 1013.93   437.1 1012.34   453.9 1011.23
   470.4 1009.45   478.5 1009.28   485.4 1009.31   518.9 1010.04   569.9 1009.85
   595.6 1010.27   621.2 1011.31   685.2 1015.20   774.8 1017.91   853.0 1020.91
  1030.6 1029.43  1056.2 1031.12  1069.0 1032.48  1072.0 1032.94  1081.8 1035.99
#Mann= 3 , 0 , 0
       0     0.1       0   470.4   0.045       0   485.4     0.1       0
Bank Sta=   470.4,   485.4
Exp/Cntr=0.3,0.1